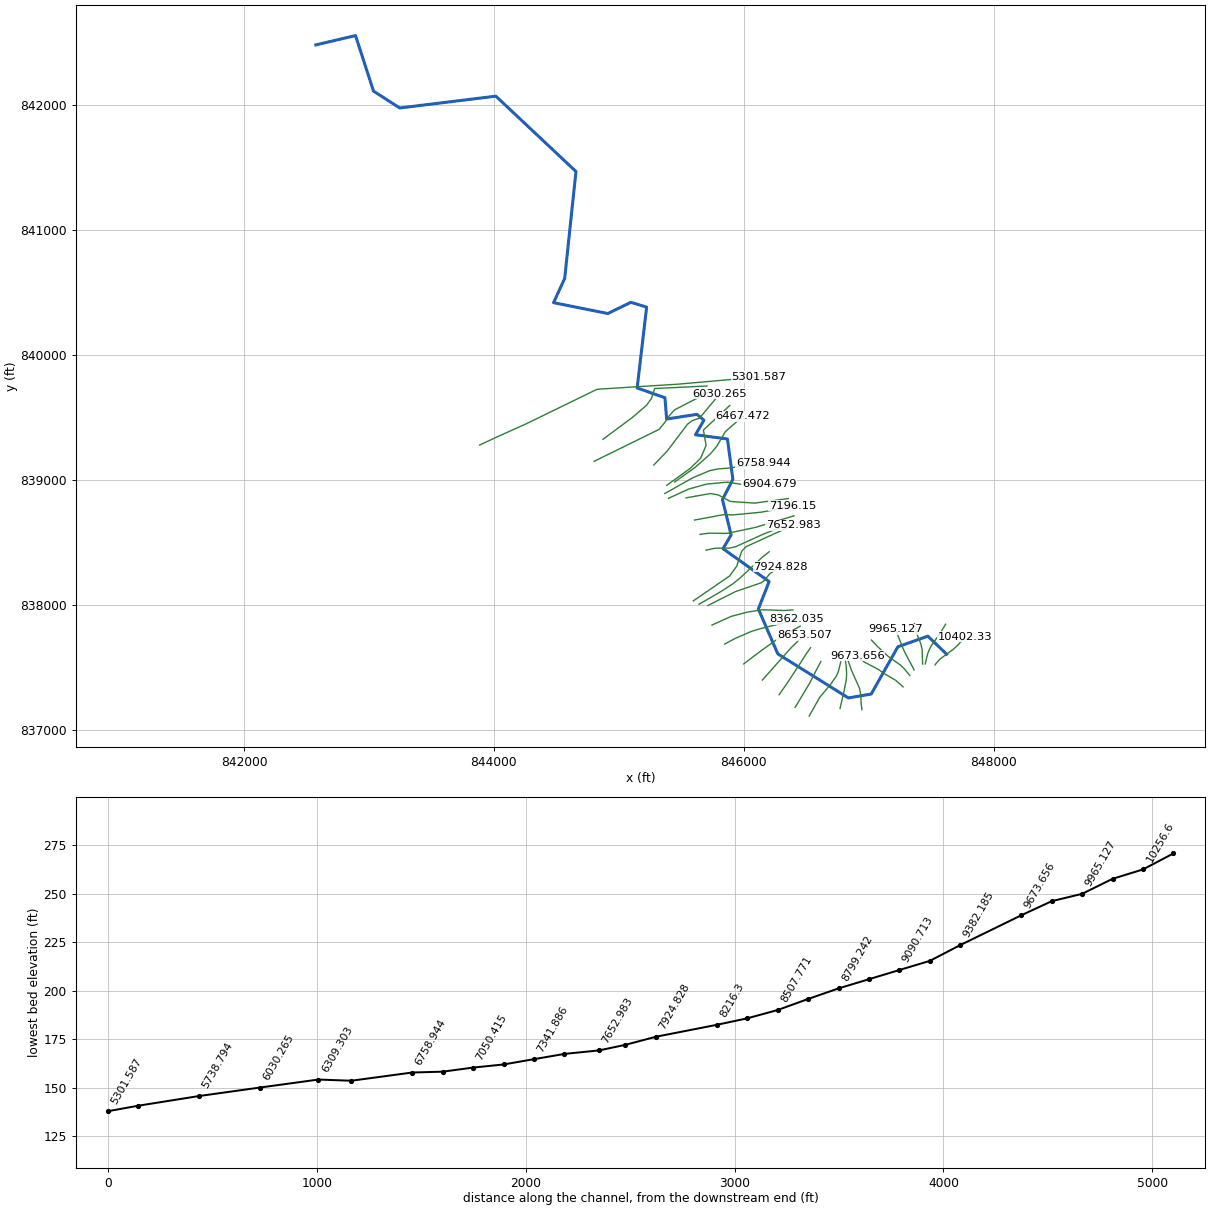
--- 18597_ras.prj (project) ---

Proj Title=18597
Current Plan=p01
Default Exp/Contr=0.3,0.1
English Units
Geom File=g01
Flow File=f01
Plan File=p01
Y Axis Title=Elevation
X Axis Title(PF)=Main Channel Distance
X Axis Title(XS)=Station
BEGIN DESCRIPTION:
RFD model 18597 exported to HEC-RAS
END DESCRIPTION:

--- 18597_ras.p01 (plan) ---

Plan Title=Plan 01
Program Version=4.10
Short Identifier=Plan 01
Geom File=g01
Flow File=f01
Subcritical Flow
Calc Critical at every XS
Secant Critical Depth

--- 18597_ras.f01 (steady flow) ---

Flow Title=Flow 01
Program Version=5.01
Number of Profiles= 6
Profile Names=10yr,25yr,50yr,100yr,100plus,500yr
River Rch & RM=18597,33,10402.33
 1379.48 1886.08 2301.86 2586.74 3776.64 4129.59
River Rch & RM=18597,33, 10256.6
 1382.79 1891.25 2308.67 2594.91 3788.57 4142.62
River Rch & RM=18597,33,10110.86
 1386.06 1896.36 2315.43 2603.04 3800.44 4155.62
River Rch & RM=18597,33,9965.127
 1389.92 1902.27 2323.15 2612.23 3813.86 4170.05
River Rch & RM=18597,33,9819.392
 1393.36 1907.56 2330.08 2620.49 3825.91 4183.03
River Rch & RM=18597,33,9673.656
 1397.34 1913.59 2337.91 2629.77 3839.46 4197.42
River Rch & RM=18597,33,9382.185
 1409.12  1931.3 2360.84 2656.85 3878.99 4239.06
River Rch & RM=18597,33,9236.449
 1414.07  1938.9 2370.79 2668.71 3896.31 4257.67
River Rch & RM=18597,33,9090.713
  1416.6 1942.85 2376.01 2674.98 3905.48 4267.68
River Rch & RM=18597,33,8944.978
 1511.29 2085.16 2560.17 2892.52 4223.08 4599.97
River Rch & RM=18597,33,8799.242
 1513.47 2088.53 2564.61 2897.84 4230.84 4608.29
River Rch & RM=18597,33,8653.507
 1521.77  2101.4 2581.55 2918.15  4260.5 4640.14
River Rch & RM=18597,33,8507.771
 1525.68 2107.49  2589.6 2927.81 4274.61 4655.35
River Rch & RM=18597,33,8362.035
 1533.02 2118.98 2604.82 2946.14 4301.36 4684.32
River Rch & RM=18597,33,  8216.3
 1535.06 2122.21 2609.11 2951.33 4308.94 4692.58
River Rch & RM=18597,33,7924.828
 1539.83 2129.74 2619.13 2963.44 4326.62 4711.84
River Rch & RM=18597,33,7779.093
 1553.54 2151.31 2647.79 2998.03 4377.13  4766.7
River Rch & RM=18597,33,7487.622
 1558.64 2159.36 2658.49 3010.96    4396 4787.21
River Rch & RM=18597,33,7341.886
 1567.82 2173.83 2677.72 3034.19 4429.92 4824.04
River Rch & RM=18597,33, 7196.15
 1571.22 2179.18 2684.84 3042.79 4442.47 4837.66
River Rch & RM=18597,33,7050.415
 1572.92 2181.86  2688.4 3047.08 4448.74 4844.46
River Rch & RM=18597,33,6904.679
 1576.66 2187.74 2696.22 3056.53 4462.53 4859.41
River Rch & RM=18597,33,6758.944
 1577.68 2189.35 2698.35  3059.1 4466.29 4863.48
River Rch & RM=18597,33,6467.472
 1631.76 2274.43  2811.4 3195.64 4665.63 5078.85
River Rch & RM=18597,33,6309.303
 1633.62 2277.44 2815.46  3200.6 4672.88 5086.86
River Rch & RM=18597,33,6030.265
 1634.24 2278.44 2816.81 3202.26  4675.3 5089.53
River Rch & RM=18597,33,5738.794
 1637.03 2282.96  2822.9  3209.7 4686.16 5101.52
River Rch & RM=18597,33,5447.323
 1645.05 2295.95 2840.44 3231.14 4717.47 5136.12
River Rch & RM=18597,33,5301.587
  1647.2 2299.43 2845.14  3236.9 4725.87 5145.42
Boundary for River Rch & Prof#=18597,33,1
Up Type= 0
Dn Type= 2
Boundary for River Rch & Prof#=18597,33,2
Up Type= 0
Dn Type= 2
Boundary for River Rch & Prof#=18597,33,2
Up Type= 0
Dn Type= 2
Boundary for River Rch & Prof#=18597,33,2
Up Type= 0
Dn Type= 2
Boundary for River Rch & Prof#=18597,33,2
Up Type= 0
Dn Type= 2
Boundary for River Rch & Prof#=18597,33,2
Up Type= 0
Dn Type= 2

--- 18597_ras.g01 (geometry) ---

Geom Title=18597
Program Version=4.10

River Reach=18597,33
Reach XY= 30
847623.948307546837607.136627051847473.832429319837751.641768928
847233.838749591837666.845271674847020.282180282837288.444601812
846837.214878085837257.278186748846272.808202148837609.693492945
846116.891683459837969.466019274846203.275522026  838188.9173797
845833.930731955 838451.84578013845898.947738499838561.618948008
 845829.66388473838845.097508036 845912.95669088 839006.68555199
845869.308256777839330.135621216845613.654191554839363.867227013
845680.989767849839480.701095726845624.775513471839527.304433407
845382.743480861839489.700700004845369.173175187839660.310818693
845146.662874282839738.551675377845222.635359198840385.683200983
845096.244315892840424.182444133844912.272621188840334.296431429
844477.479820639840421.171808977844566.620033295 840615.01051029
844656.847372147841471.155689579 844015.60458556842074.249034085
843246.139226199841979.680247704843036.347017737842114.785578606
842892.268947453842559.342128789842574.643588069842484.614897918

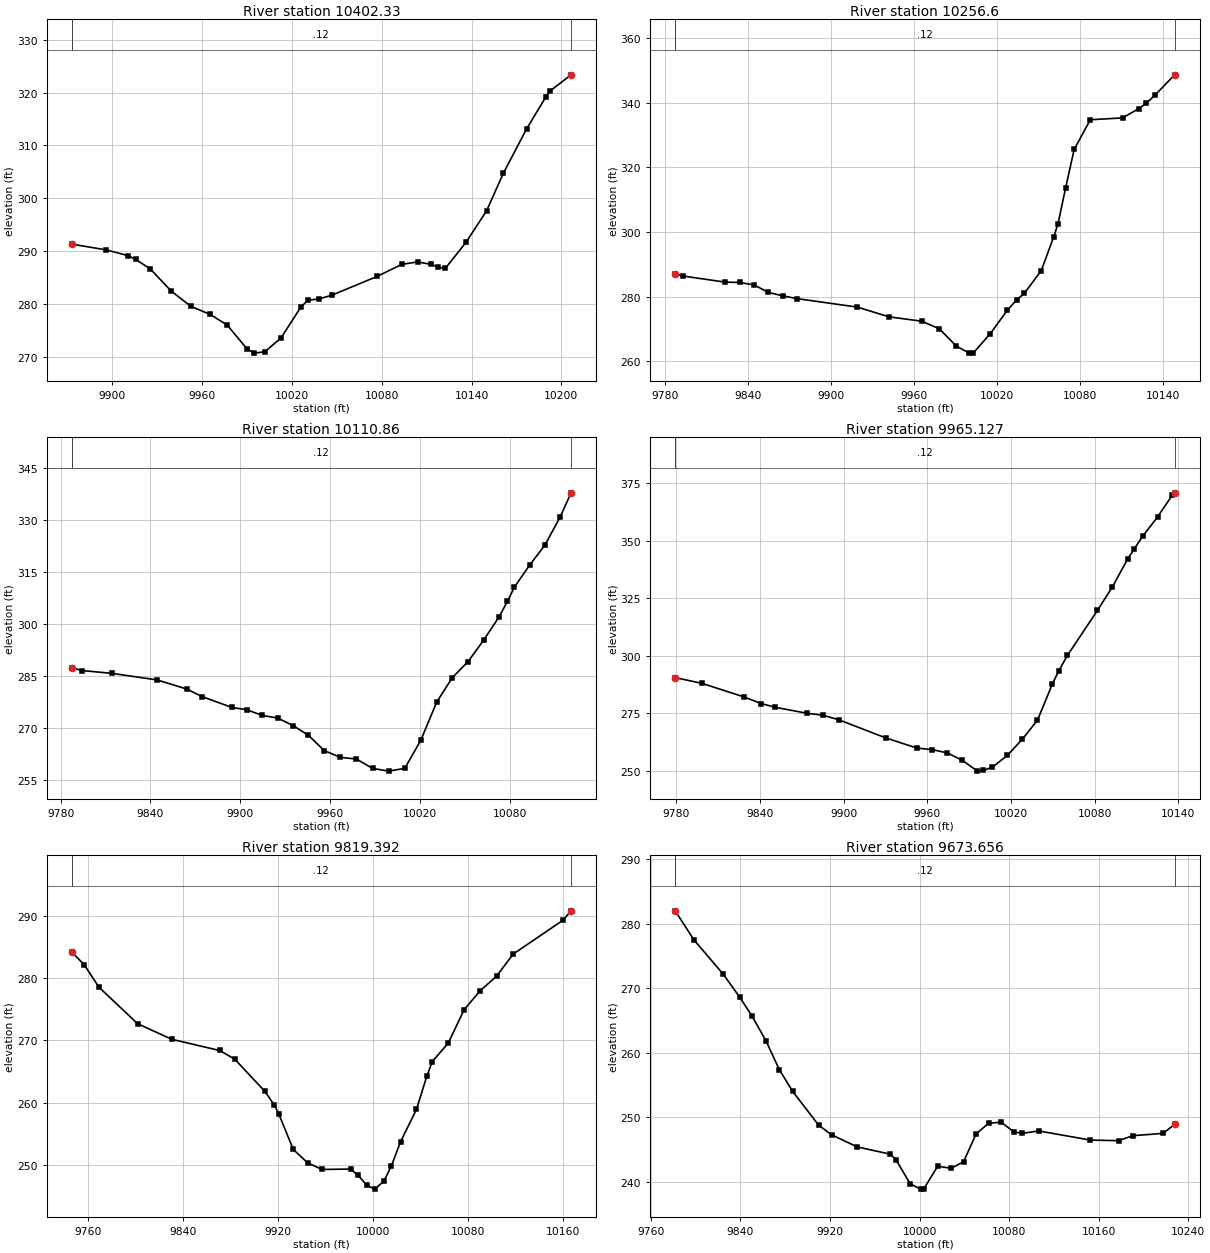
Type RM Length L Ch R = 1 ,10402.33,145.735600,145.735600,145.735600
XS GIS Cut Line= 6
847531.607888967837521.634777457847543.503856284837538.991565179
847570.583332629837568.173811843847676.857819629837646.518677283
847711.507503105837677.935338349847773.984596341837747.813812056
#Sta/Elev= 30
9872.905291.33729896.147290.23529910.849289.13469915.786288.4302 9925.55 286.609
9939.495282.43389952.484279.57589965.472278.02669976.788276.02989989.851 271.587
9994.608270.713810001.87270.962810012.75 273.58710025.85279.359910030.66280.7306
10038.33280.972610047.05281.716110076.91285.221910093.43287.509110103.91287.9646
10112.69287.522210117.75286.986910122.46286.743810136.29291.667610150.11297.6704
10161.33304.796510176.91313.207210189.76319.248910192.48320.318310206.48323.3641
#Mann= 3 , 0 , 0
9872.905    0.12       09872.905    0.12       010206.48    0.12       0
#XS Ineff= 2 , 0
       0                               0
Bank Sta=9872.905,10206.48
Exp/Cntr=0.3,0.1

Type RM Length L Ch R = 1 , 10256.6,145.735700,145.735700,145.735700
XS GIS Cut Line= 6
847452.872022581837529.258280538847472.360700377837611.504656868
847487.328463693837648.918786465847502.997628289 837677.86423512
847570.561151258837772.341556659847615.651251331837847.337628937
#Sta/Elev= 30
9787.232286.96979793.008286.3456 9823.61284.44769833.894284.35569844.298283.6007
9854.702281.27049865.106280.21239875.639279.32749919.086276.72079941.828 273.723
9965.714272.3418 9978.45269.98589990.746 264.62610000.12262.458510003.02262.5186
10015.31   268.510027.61275.7238 10034.5279.036510039.91280.965310052.21288.0515
10061.24  298.5410064.34 302.59910069.84313.705610076.01325.587510087.68334.7898
10111.02335.361610122.69338.207210128.03339.830810134.36342.348710148.74348.7099
#Mann= 3 , 0 , 0
9787.232    0.12       09787.232    0.12       010148.74    0.12       0
#XS Ineff= 2 , 0
       0                               0
Bank Sta=9787.232,10148.74
Exp/Cntr=0.3,0.1

Type RM Length L Ch R = 1 ,10110.86,145.735600,145.735600,145.735600
XS GIS Cut Line= 6
847431.845660989837528.006711396847427.888814025837644.037944287
847417.545859089837689.339503027847389.368294129837759.916204662
847376.918899387  837800.6497308847366.799186705837852.122407836
#Sta/Elev= 30
9787.342287.43969794.335286.63919814.335 285.8239844.336283.94899864.353281.2997
9874.386279.13729894.453275.99519904.508275.31739914.765273.68179925.022272.9391
 9935.28270.76669945.537267.95429956.078263.56779966.837261.59349977.595261.1286
9988.354258.41939999.113257.6286 10009.9258.419710020.68  266.57 10031.3277.5943
10041.75284.630310052.21289.225710062.67295.451710073.01302.168710078.52306.6221
 10083.2310.717610093.39 317.08110103.58322.836910113.77330.984310121.03 337.903
#Mann= 3 , 0 , 0
9787.342    0.12       09787.342    0.12       010121.03    0.12       0
#XS Ineff= 2 , 0
       0                               0
Bank Sta=9787.342,10121.03
Exp/Cntr=0.3,0.1

Type RM Length L Ch R = 1 ,9965.127,145.735600,145.735600,145.735600
XS GIS Cut Line= 6
847362.994997197837481.108967658847357.143704495837494.934279559
847297.540498506 837605.77326097847279.307426826837643.747800554
847265.440976844837677.876953398  847214.5339547837806.502266648
#Sta/Elev= 30
9779.176290.53049798.714287.96769828.325 282.1539840.943279.23629851.034  277.62
9873.742275.01659885.096274.1852 9896.45272.20169930.272264.30479952.458259.9059
9963.513259.22319974.307257.79169985.101254.57729995.895249.885310000.23250.2148
10006.66251.606410017.42256.745510028.18263.811310038.95 271.99510049.71287.8371
10054.33293.562110060.47300.1892   10082319.760410092.76330.000710103.53341.9694
10108.39346.475910114.29351.861110125.05360.304710135.74369.906110137.34370.8257
#Mann= 3 , 0 , 0
9779.176    0.12       09779.176    0.12       010137.34    0.12       0
#XS Ineff= 2 , 0
       0                               0
Bank Sta=9779.176,10137.34
Exp/Cntr=0.3,0.1

Type RM Length L Ch R = 1 ,9819.392,145.735600,145.735600,145.735600
XS GIS Cut Line= 6
847329.460383748 837436.39614972847287.003840521837488.884123232
847254.099144548837520.139494087847154.413854006837591.164419339
847072.455726051837667.008372708847022.328824591 837720.31162536
#Sta/Elev= 30
9746.383284.21389757.002282.14069769.343 278.5499801.865272.68549830.524270.1773
9870.939268.37439883.675266.9813 9908.84261.8471 9916.99259.61269920.888258.1176
9932.936252.47419944.983250.33329957.031249.26499981.127249.32579987.351248.3523
9994.928 246.71310001.51246.102710009.24247.391910015.58249.860110023.22253.7135
10036.61258.9104 10045.4264.275910049.99266.602710063.38269.570310076.76274.9302
10090.15277.959210104.02280.301810118.06283.870910159.78289.276410166.77290.8115
#Mann= 3 , 0 , 0
9746.383    0.12       09746.383    0.12       010166.77    0.12       0
#XS Ineff= 2 , 0
       0                               0
Bank Sta=9746.383,10166.77
Exp/Cntr=0.3,0.1

Type RM Length L Ch R = 1 ,9673.656,291.471300,291.471300,291.471300
XS GIS Cut Line= 6
847275.816334112837345.736537601847215.852281784 837398.48500051
847119.398734622837455.551423911847078.754566205837484.682384701
  846962.9784341837545.773940391846908.049069244837593.570814606
#Sta/Elev= 30
9781.694282.00099798.359277.50179824.667 272.1599839.359268.59029850.282265.6941
9862.757261.83599874.665257.37139886.572253.99589909.883248.73689921.388247.2499
9944.398245.36829973.851244.24789979.265243.28699991.571239.6479   10001238.8241
10003.95238.9143 10016.2 242.38710028.06242.054410039.25243.057110050.43247.3769
10061.62249.039410072.81249.2154   10084247.730310091.49247.474310106.37247.8519
10152.48246.434910177.73 246.33910190.46247.117110217.57  247.4710227.84248.8841
#Mann= 3 , 0 , 0
9781.694    0.12       09781.694    0.12       010227.84    0.12       0
#XS Ineff= 2 , 0
       0                10091.43       0
Bank Sta=9781.694,10227.84
Exp/Cntr=0.3,0.1

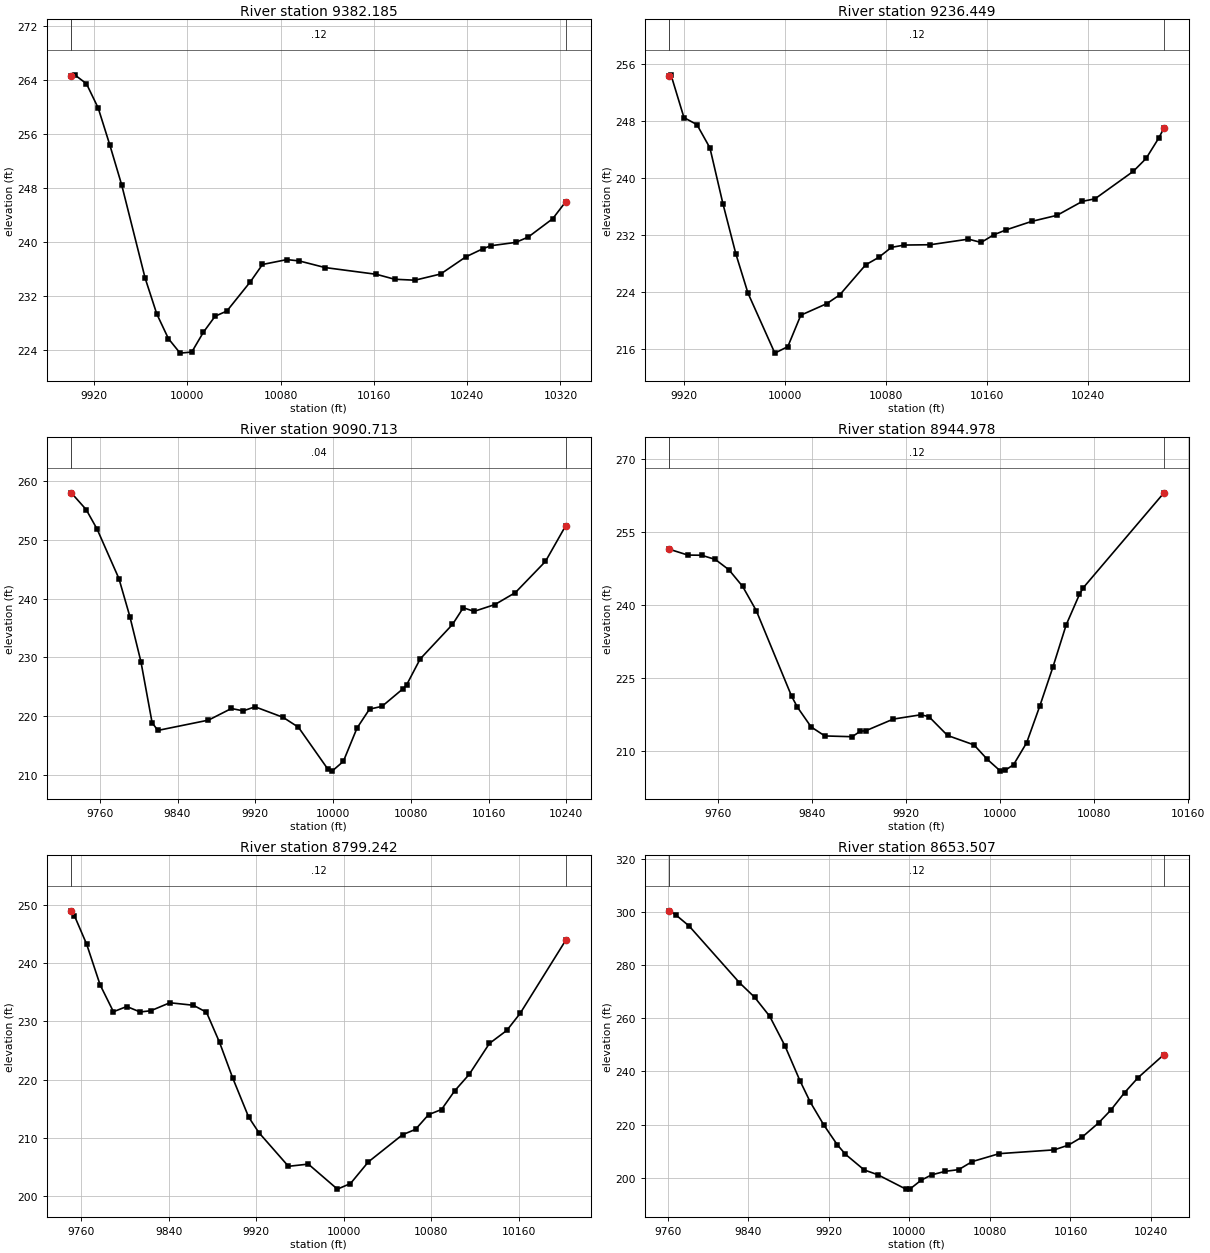
Type RM Length L Ch R = 1 ,9382.185,145.735600,145.735600,145.735600
XS GIS Cut Line= 6
 846945.80970879837162.065083922 846939.88055585837210.348664634
846936.044033755837285.124033372846927.168055031837333.124909865
846864.591285431837473.189969097846831.641526947837565.786253772
#Sta/Elev= 30
9900.348264.59629903.305264.7595 9913.38263.43969923.456259.83829933.531254.2958
9943.606248.43829963.671234.64839973.689 229.3199983.706225.64589993.723223.5041
10003.73223.665910013.74226.612910023.75228.975410033.83229.742710054.09234.1025
10064.39236.644610085.36237.369910095.97237.1698   10118236.1911 10162.1235.1888
10177.82234.453410195.18234.315210217.24235.233710238.89237.781110253.49238.9783
10260.26239.423310281.63239.918410292.31240.704310313.36243.4276 10324.6245.9664
#Mann= 3 , 0 , 0
9900.348    0.12       09900.348    0.12       0 10324.6    0.12       0
#XS Ineff= 2 , 0
       0                10154.52       0
Bank Sta=9900.348,10324.6
Exp/Cntr=0.3,0.1

Type RM Length L Ch R = 1 ,9236.449,145.735600,145.735600,145.735600
XS GIS Cut Line= 6
 846770.71206976837173.816436918846804.245552636837316.427652756
846820.337981983837400.836081885846823.526792584837447.015262493
846820.424016942837508.542953129846813.063397727 837559.03057042
#Sta/Elev= 30
 9908.44254.37729909.656254.49539919.931248.48259930.206247.49479940.481244.2235
9950.756236.38719961.032229.30389970.596223.80959991.857215.372810002.13216.2882
 10012.4220.705310032.94222.3281 10043.2223.558110063.71  227.7810073.93228.8182
10084.16230.243610094.38230.566310114.75230.609810145.07231.3968 10155.1230.9309
10165.12232.006210175.15232.716110195.18233.894810215.21234.746710235.23236.7077
10245.25237.069210275.53240.927610285.64242.733310295.74245.619810299.82247.0164
#Mann= 3 , 0 , 0
 9908.44    0.12       0 9908.44    0.12       010299.82    0.12       0
#XS Ineff= 2 , 0
       0                10157.22       0
Bank Sta=9908.44,10299.82
Exp/Cntr=0.3,0.1

Type RM Length L Ch R = 1 ,9090.713,145.735700,145.735700,145.735700
XS GIS Cut Line= 6
846523.351190201837111.429666357846607.420956097837260.415652678
846696.262091826837367.973344053846739.381222775837429.318409142
846755.992303236837463.774635651 846776.38808269837545.694092225
#Sta/Elev= 30
9730.689257.98429745.957 255.1479757.208251.8352 9779.71243.40459790.961236.9508
9802.374229.25749813.853218.90199819.748217.57889871.834219.32979895.463221.3092
  9907.5220.9044  9919.8221.59329948.598219.80629964.381218.12479994.847210.9568
    9999210.657410010.61212.312410024.69217.985110037.52221.196110050.42221.6771
10072.07224.676710075.74225.337310089.64 229.729 10122.9235.5998   10134 238.444
 10145.1237.8242 10166.6238.988610187.55241.014610218.53 246.31510239.48252.4201
#Mann= 3 , 0 , 0
9730.689    0.04       09730.689    0.04       010239.48    0.04       0
#XS Ineff= 2 , 0
       09909.803        10135.37       0
Bank Sta=9730.689,10239.48
Exp/Cntr=0.3,0.1

Type RM Length L Ch R = 1 ,8944.978,145.735600,145.735600,145.735600
XS GIS Cut Line= 6
846411.560561275837181.559191325846525.558010379837371.849023003
 846552.63889933837423.892641791846553.470210574 837425.71168594
846573.197237546837465.682654176846617.233440165837548.489304145
#Sta/Elev= 30
9718.509251.48979734.177 250.3019745.834250.26339757.491249.40889769.148247.2735
9780.805243.86089792.463 238.8589822.495221.29379827.434219.04839839.091214.9959
9850.748213.14689874.063212.9885 9880.87 214.111 9885.72214.22549909.034216.6103
9932.348217.48929939.246217.12989955.157213.24829977.703211.30669988.975208.3473
10000.22205.918910004.46 206.12510011.36207.241810022.51211.755410033.66219.2758
10044.81227.264410056.13 235.95910067.45242.227610070.71 243.59810139.36263.0862
#Mann= 3 , 0 , 0
9718.509    0.12       09718.509    0.12       010139.36    0.12       0
#XS Ineff= 2 , 0
       09921.528                       0
Bank Sta=9718.509,10139.36
Exp/Cntr=0.3,0.1

Type RM Length L Ch R = 1 ,8799.242,145.735600,145.735600,145.735600
XS GIS Cut Line= 6
846283.322762266837283.409028321846345.129386566837371.801233394
846422.249244865837489.032867384846423.389308928837490.676112325
846499.172104831837608.277796529846534.851941359837659.177019539
#Sta/Elev= 30
9750.819248.99649753.746248.14039764.962243.22729777.164236.29449789.367 231.661
9801.569232.55729813.771231.61869823.549231.8293    9841233.20329862.505232.7709
9874.475231.56929886.445226.38359898.415220.29389913.028213.56189922.354210.9004
9949.419205.10279967.614205.48189994.173201.182910006.14202.138110022.43205.8489
10053.73210.525710065.63211.450210077.52213.973710089.42214.863110101.32218.0388
10114.74220.9035 10133.2226.211510149.11  228.4510161.33231.382710203.06243.9575
#Mann= 3 , 0 , 0
9750.819    0.12       09750.819    0.12       010203.06    0.12       0
#XS Ineff= 2 , 0
       0                               0
Bank Sta=9750.819,10203.06
Exp/Cntr=0.3,0.1

Type RM Length L Ch R = 1 ,8653.507,145.735600,145.735600,145.735600
XS GIS Cut Line= 6
846148.759244412837400.446771274846306.654183346837577.789982213
846307.927476235837579.332293861846378.094027086837657.578958503
846449.113757212837727.566218716846484.108278983837759.086127555
#Sta/Elev= 30
9761.552300.35599767.649298.90189781.038294.67599831.091273.34769846.129267.8835
9861.167260.71319876.206 249.6829891.244236.4788 9901.54228.40269914.929219.8422
9928.319 212.4089936.359208.85219955.097202.92899968.486201.15069996.512195.7246
   10001195.905310011.59199.063410022.04201.085810035.48202.410310048.91203.0501
10062.34206.0706 10089.2209.063710143.87210.487810157.91 212.25810171.95215.3849
10187.91220.612810200.03225.407110213.73231.993210227.19 237.64110252.91246.3131
#Mann= 3 , 0 , 0
9761.552    0.12       09761.552    0.12       010252.91    0.12       0
#XS Ineff= 2 , 0
       0                               0
Bank Sta=9761.552,10252.91
Exp/Cntr=0.3,0.1

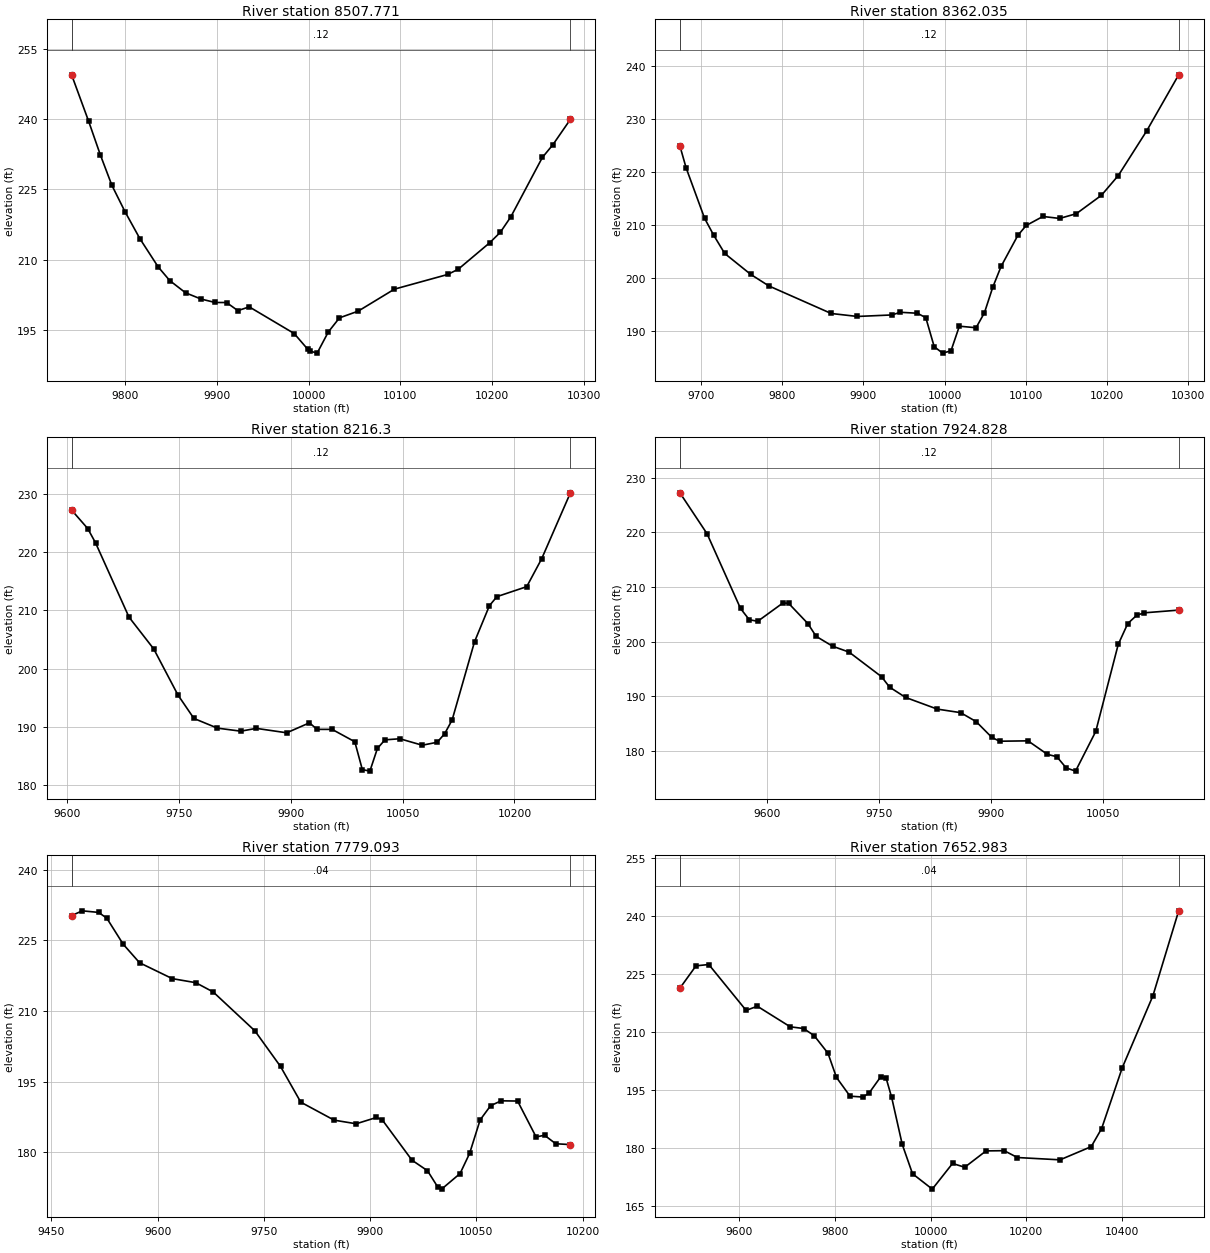
Type RM Length L Ch R = 1 ,8507.771,145.735700,145.735700,145.735700
XS GIS Cut Line= 6
846000.213035443837529.480554475846085.993743585837595.562303383
846202.734243984837680.997475825846256.839054379837718.508292614
846304.372080976837748.656887515846451.637095787837831.709849093
#Sta/Elev= 30
9741.549249.43369760.215239.47879772.838232.38199785.461225.86679799.752220.2461
9816.138214.43849835.954208.45079848.577205.52989865.812  202.929882.745 201.585
9898.168200.8463 9910.56200.84149922.952199.10999935.344199.9159 9984.34 194.228
    9999190.905110001.58190.4846 10009.4190.041710021.57194.547910033.74197.5667
10054.18199.002910093.68203.692410151.78206.826210163.26207.934710197.71 213.605
10209.19 215.81410220.67219.118710255.11231.800810266.59 234.51810285.69 239.931
#Mann= 3 , 0 , 0
9741.549    0.12       09741.549    0.12       010285.69    0.12       0
#XS Ineff= 2 , 0
       09866.996                       0
Bank Sta=9741.549,10285.69
Exp/Cntr=0.3,0.1

Type RM Length L Ch R = 1 ,8362.035,145.735600,145.735600,145.735600
XS GIS Cut Line= 6
845848.253429987837688.700224268845929.932180346837732.953876189
846060.357872776837789.409003699846146.334452098837815.523689632
846329.216978053837859.997935337846426.214622826837888.568713333
#Sta/Elev= 30
9674.038224.88219681.715220.73699704.461211.21389715.834207.98329729.242204.5787
9761.326200.62429783.547198.45699860.385 193.2499892.617 192.6889935.036 192.972
9945.554193.47429966.528193.29459976.891192.45979987.254186.97989997.617185.7647
10007.93186.199210018.22190.8506 10038.8190.555310049.09193.378710059.38198.2088
10069.67202.148810090.26207.994310100.55209.860810121.13211.565610141.71211.1925
10162.29212.088210193.21215.561510213.97219.289310248.85227.695810288.35238.3046
#Mann= 3 , 0 , 0
9674.038    0.12       09674.038    0.12       010288.35    0.12       0
#XS Ineff= 2 , 0
       09923.134                       0
Bank Sta=9674.038,10288.35
Exp/Cntr=0.3,0.1

Type RM Length L Ch R = 1 ,  8216.3,291.471200,291.471200,291.471200
XS GIS Cut Line= 6
845745.680742167837840.659761785 845900.64275551837910.522113665
846028.313079083837944.030512691  846150.1208437837962.999390545
846324.312426877837957.138442981846393.393136373837961.975908821
#Sta/Elev= 30
9605.904227.2157 9627.49 224.0519638.051221.58499682.886208.85129716.118203.3821
9748.565195.4858 9769.98191.46049801.519189.79889832.923189.27559853.604189.7583
9894.524188.99849925.047190.71159935.177189.58559955.437189.58369985.826187.4632
9995.956182.681510006.08182.420910016.17186.312210026.26  187.7910046.31187.9751
10076.33186.865810096.37187.374510106.38188.8374 10116.4191.193510146.45204.6126
10166.47210.816810176.47212.359710216.49214.075110236.51218.849610275.09230.1752
#Mann= 3 , 0 , 0
9605.904    0.12       09605.904    0.12       010275.09    0.12       0
#XS Ineff= 2 , 0
       09930.849                       0
Bank Sta=9605.904,10275.09
Exp/Cntr=0.3,0.1

Type RM Length L Ch R = 1 ,7924.828,145.735700,145.735700,145.735700
XS GIS Cut Line= 6
845712.818179839837997.124092273845932.606961476838107.842194835
846140.602655024   838179.423985 846161.39708269838195.094844574
846209.518111927838252.399182944846292.759223565838308.799218314
#Sta/Elev= 30
9483.693227.22159520.071219.73399564.929206.0497 9576.59203.99919587.894203.7012
9621.806 207.0689629.428206.98279655.102203.29449666.159200.95489688.272 199.143
9710.385198.06129753.869 193.5569764.594191.65099786.044189.76839828.437187.6317
 9859.74186.98329880.608185.33669901.476 182.4649911.911181.75239950.016181.8213
9976.005179.34469988.621 178.91910001.14176.868810013.68 176.27810040.76183.5424
10070.89199.482310083.66203.2981 10095.8204.825610105.83205.256110151.86205.7525
#Mann= 3 , 0 , 0
9483.693    0.12       09483.693    0.12       010151.86    0.12       0
#XS Ineff= 2 , 0
       0                               0
Bank Sta=9483.693,10151.86
Exp/Cntr=0.3,0.1

Type RM Length L Ch R = 1 ,7779.093,126.109600,126.109600,126.109600
XS GIS Cut Line= 6
845641.956936707838007.203164834 845816.87711954838108.451030939
845916.342033132838173.288143927845972.465544455838219.018123298
 846149.54161642 838384.81449478846203.290066219838427.080477198
#Sta/Elev= 30
9478.555230.29029493.625231.30479516.734230.96639528.289229.72979551.397224.2028
9574.506220.26479620.724216.88449653.814216.02669678.495214.04979737.355205.7793
9773.535 198.2079802.135190.61739849.291186.78919880.389186.02059909.035187.3645
9917.264186.83519959.168178.27349981.042 176.0429995.967172.4734   10001172.1235
10027.06175.437610040.53179.719910055.37186.8337 10070.2189.869610085.04190.9036
10108.29190.8535 10134.4183.222410146.33  183.5810162.14181.770610182.85181.5968
#Mann= 3 , 0 , 0
9478.555    0.04       09478.555    0.04       010182.85    0.04       0
#XS Ineff= 2 , 0
       0                               0
Bank Sta=9478.555,10182.85
Exp/Cntr=0.3,0.1

Type RM Length L Ch R = 1 ,7652.983,165.361600,165.361600,165.361600
XS GIS Cut Line= 6
845596.100342633838034.011788192845887.534516145838233.917643997
845943.453635258838311.716222166845983.416726171838430.774993047
846018.118115639838467.912411163846395.413527601 838639.81240115
#Sta/Elev= 30
9475.342221.29989509.006 227.0859535.764227.43019613.843215.55089637.288216.6239
9706.181211.2904 9734.09210.85279756.308 208.9849785.084204.43869802.807198.1769
9831.205193.32689857.302193.10519870.351194.0176 9894.93198.27069906.822197.9201
9918.238193.01839940.301180.86019961.848173.236710003.17169.247110045.56175.8934
10071.06174.9152 10115.7179.150210153.53179.206810181.28177.4315 10270.4176.8356
10335.64 180.25410357.37184.935310400.42200.6572 10464.6219.315110518.53241.3343
#Mann= 3 , 0 , 0
9475.342    0.04       09475.342    0.04       010518.53    0.04       0
#XS Ineff= 2 , 0
       0                               0
Bank Sta=9475.342,10518.53
Exp/Cntr=0.3,0.1

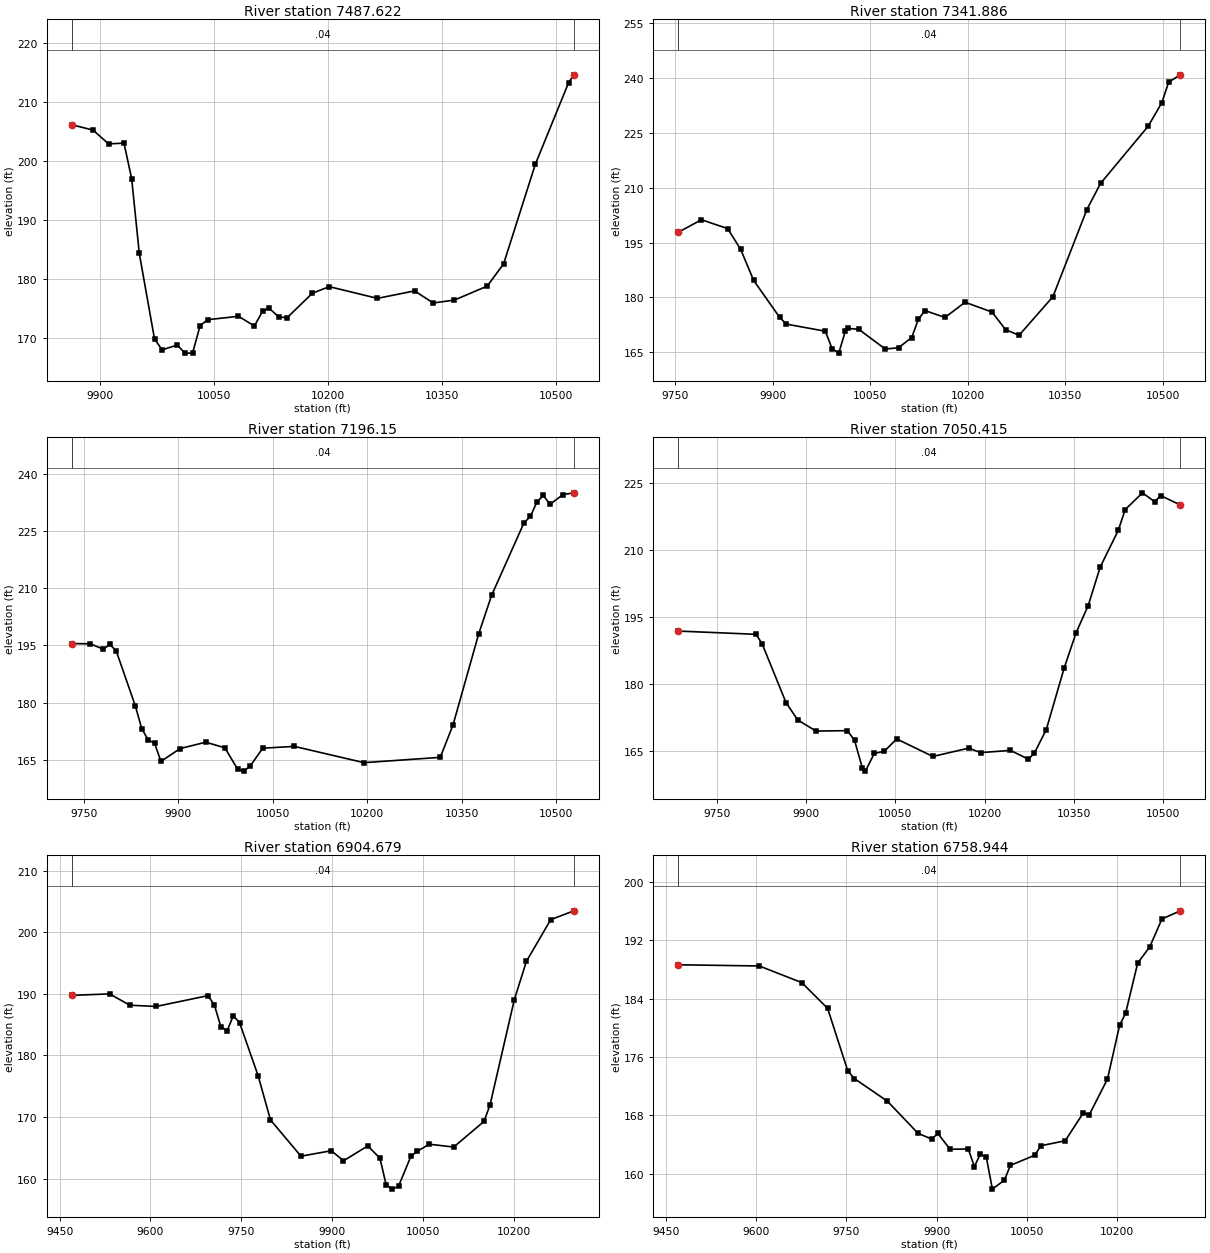
Type RM Length L Ch R = 1 ,7487.622,145.735600,145.735600,145.735600
XS GIS Cut Line= 6
845697.933845163838440.050907457845769.496506994838455.680708344
 845888.40452569838456.915513987845937.906039307838468.749920546
846157.645653817838568.773811881846321.410827445838632.960038331
#Sta/Elev= 30
 9862.47206.13969890.488 205.2319910.842202.90229931.197203.01889941.292197.0036
9951.319184.34539971.374169.83479981.401168.0103 10001.4168.816110011.41167.4545
10021.42 167.44910031.43172.111310041.44173.1126 10081.9173.689210102.82172.0444
10113.53 174.529 10122.3175.036410135.15173.558110145.96173.461310179.17177.5996
10201.32178.711410264.79176.725810313.62177.9915 10338.1175.942710366.09176.4384
10409.31178.808510430.85182.588310472.53199.431210516.39213.278710523.25214.5949
#Mann= 3 , 0 , 0
 9862.47    0.04       0 9862.47    0.04       010523.25    0.04       0
#XS Ineff= 2 , 0
       0                               0
Bank Sta=9862.47,10523.25
Exp/Cntr=0.3,0.1

Type RM Length L Ch R = 1 ,7341.886,145.735700,145.735700,145.735700
XS GIS Cut Line= 6
845649.694877763838566.599886863845724.349560526838576.169011854
845848.364253775838574.221818562845877.170261586838576.646783259
846094.668383898838622.595760189846402.032175031 838714.78673662
#Sta/Elev= 30
9755.075197.82439790.794201.26249831.032198.83079851.036193.14939871.041184.6297
9911.069 174.5159921.078 172.6959981.204170.7443 9991.46165.9935 10001.8164.7495
10012.13170.891410016.66 171.52810032.73171.240410073.32165.864110093.62166.2259
10113.92 169.02610124.07173.986210134.29176.395510165.09174.513610195.88178.6721
10237.35175.997810258.15171.180410278.95169.640610330.94180.204610383.15204.0556
 10404.1211.200310477.45226.8877 10498.4 233.33810508.88238.945510526.73240.9256
#Mann= 3 , 0 , 0
9755.075    0.04       09755.075    0.04       010526.73    0.04       0
#XS Ineff= 2 , 0
       0                               0
Bank Sta=9755.075,10526.73
Exp/Cntr=0.3,0.1

Type RM Length L Ch R = 1 , 7196.15,145.735600,145.735600,145.735600
XS GIS Cut Line= 6
845606.015411193838681.187578375845836.327337345838723.768597301
845916.174647951 838722.51767149846136.881663212838743.771433149
846277.273870078838768.759436375 846391.83575295838797.196598513
#Sta/Elev= 30
9731.285195.51719760.927195.43459781.381194.02689791.584195.29059801.736193.6167
9832.195179.10549842.348173.15129852.501170.22649862.654169.31749872.806164.5697
9903.265167.93979943.876 169.6049974.216168.13819994.265162.564110004.32162.0107
10014.37163.340210034.38168.039110084.53168.504710194.96164.233310316.03165.6308
10336.29174.164610377.01198.058110397.41208.1453 10448.8227.196610459.11228.9111
10469.41232.700210479.71234.399910490.02232.062810510.62  234.6210527.97235.0909
#Mann= 3 , 0 , 0
9731.285    0.04       09731.285    0.04       010527.97    0.04       0
#XS Ineff= 2 , 0
       0                10175.77       0
Bank Sta=9731.285,10527.97
Exp/Cntr=0.3,0.1

Type RM Length L Ch R = 1 ,7050.415,145.735600,145.735600,145.735600
XS GIS Cut Line= 6
845538.287312227838858.863889935845734.556516585838893.671746835
845798.177959029838881.216833279845892.165175765838830.282285935
846087.287346742838816.699859511846357.223891378838853.306518101
#Sta/Elev= 30
9685.661191.77899816.362191.0508 9826.45 188.9369866.524175.77929886.088 171.886
9916.824169.38679969.687169.47329981.701167.27339994.663161.11969999.815160.4104
10014.82164.387710031.43164.847510052.39167.618410113.06163.698310173.29165.5537
10193.31164.557710243.31165.050510273.35163.086410283.37164.415110303.41169.7003
10333.47183.505610353.58191.427910373.76197.474810393.95206.104410424.23214.3271
10435.95218.998110464.95222.739710485.35220.746410495.56222.115810528.43220.0211
#Mann= 3 , 0 , 0
9685.661    0.04       09685.661    0.04       010528.43    0.04       0
#XS Ineff= 2 , 0
       0                10220.81       0
Bank Sta=9685.661,10528.43
Exp/Cntr=0.3,0.1

Type RM Length L Ch R = 1 ,6904.679,145.735600,145.735600,145.735600
XS GIS Cut Line= 6
845398.936094439838855.466243477845557.218395089838928.660318715
845701.320587636838968.882557917845868.333888163838984.618375339
845997.299070939838964.164985674 846203.01552155838969.232294996
#Sta/Elev= 30
9470.093189.7476 9532.63189.98029565.892 188.1449609.452187.94429695.013189.6993
9705.577 188.1749716.141184.68089726.488183.99989736.803186.42599747.119 185.306
9777.802176.69469798.117169.53699848.471163.64469898.642164.5318 9918.71162.8996
9958.846165.31559978.932163.31739989.104158.99529999.378158.298910009.63158.7741
10030.09163.648710040.32164.428710060.49165.587810100.69165.126910150.71169.2869
10160.72172.001710200.74189.047210220.76195.276310260.84202.029610299.02203.4633
#Mann= 3 , 0 , 0
9470.093    0.04       09470.093    0.04       010299.02    0.04       0
#XS Ineff= 2 , 0
       0                               0
Bank Sta=9470.093,10299.02
Exp/Cntr=0.3,0.1

Type RM Length L Ch R = 1 ,6758.944,291.471300,291.471300,291.471300
XS GIS Cut Line= 6
845367.956382349838893.586381217845593.777825761839020.188613786
845726.088381794839076.058046151845792.083165918839090.253580688
845878.009147854839096.880961544846155.302976758839135.403571672
#Sta/Elev= 30
9469.687188.6319 9604.74188.46769675.561186.18449718.625182.64339752.042174.1098
9763.089173.02589818.139169.92689869.234165.51949891.905164.72919902.228165.4965
9922.575163.33269952.925163.37089962.984160.96399973.044162.65239983.059162.2036
 9993.07157.865710013.11159.099710023.13161.123510063.67162.510310073.82163.8151
10114.38164.494710144.58 168.32410154.65168.085110184.85172.967710204.98180.3142
10215.05181.994510235.19188.869610255.33191.095410275.55194.911110306.18196.0295
#Mann= 3 , 0 , 0
9469.687    0.04       09469.687    0.04       010306.18    0.04       0
#XS Ineff= 2 , 0
       0                               0
Bank Sta=9469.687,10306.18
Exp/Cntr=0.3,0.1

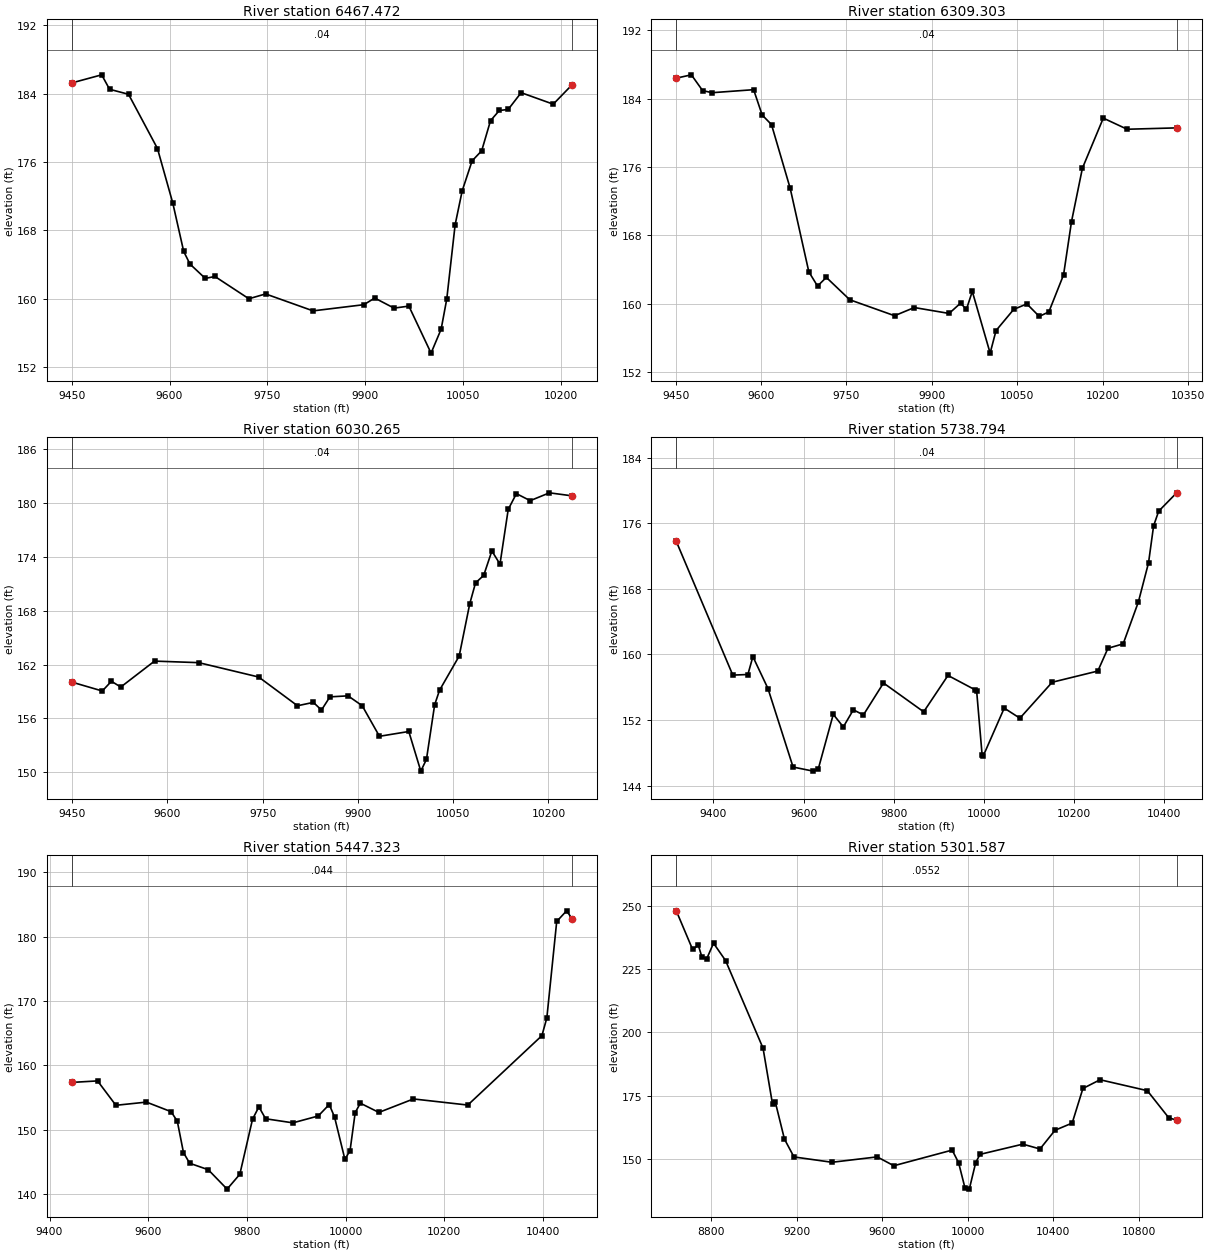
Type RM Length L Ch R = 1 ,6467.472,158.168700,158.168700,158.168700
XS GIS Cut Line= 6
845446.992600936838985.913509911845608.837122492 839101.06489413
845732.523783653839210.319393162845784.230295489839271.536573562
845852.475525285839388.834079145845993.214316259 839511.64290033
#Sta/Elev= 30
 9449.91185.25299495.904 186.2049508.005184.51299537.075183.92869581.451177.5808
 9604.95171.1978 9621.69165.53189631.329164.05859654.737162.38429669.605 162.607
9721.632160.00039747.282160.56569820.035158.58419897.957159.30699914.614160.0844
9944.264 158.9069966.984159.1405   10001153.6386 10016.5156.453810025.08159.9655
10037.92168.664310048.74172.628510063.93 176.13610078.63177.315810092.17180.8403
10105.71182.031610119.24182.150910139.14184.116110188.35182.769110217.22 185.037
#Mann= 3 , 0 , 0
 9449.91    0.04       0 9449.91    0.04       010217.22    0.04       0
#XS Ineff= 2 , 0
       0                               0
Bank Sta=9449.91,10217.22
Exp/Cntr=0.3,0.1

Type RM Length L Ch R = 1 ,6309.303,279.038200,279.038200,279.038200
XS GIS Cut Line= 6
845383.160329197 838958.82046046845570.259516845839093.689468786
845654.849018293839175.648765618845698.788306098839278.820741207
845677.028192573 839401.50513017845888.687543852839598.944122628
#Sta/Elev= 30
 9451.17186.40319477.658186.79199497.437184.94559514.043184.7016    9587185.0539
9601.955182.09339618.373180.96799651.209173.50819683.893 163.7519699.156162.0804
9714.642163.09349755.809160.47859834.433158.61159869.106159.56819930.197158.8773
9950.359160.08549960.523159.34489970.945161.453710002.24154.235210012.62156.8739
10043.67159.354110066.75159.994510088.49158.531610105.34159.057110131.16163.3918
10145.12169.623910164.24175.864510200.95181.727410242.82180.426110329.74180.5853
#Mann= 3 , 0 , 0
 9451.17    0.04       0 9451.17    0.04       010329.74    0.04       0
#XS Ineff= 2 , 0
       0                               0
Bank Sta=9451.17,10329.74
Exp/Cntr=0.3,0.1

Type RM Length L Ch R = 1 ,6030.265,291.471200,291.471200,291.471200
XS GIS Cut Line= 6
845279.840059667839121.515830084845386.978166005839232.928890615
845549.111578243839447.628450544845586.586639749839475.965740125
845645.643112311839496.779219867845808.219229593839691.638119778
#Sta/Elev= 30
9449.122160.04999497.316159.05449511.709160.13669526.434159.4941 9579.56162.3831
9649.299162.20999743.653  160.619804.764157.41029829.774157.7877 9842.54156.9315
 9855.86158.4016  9884.4158.51339906.666 157.4179933.865154.01019980.075154.5444
    9999150.131710007.91151.448810020.79157.516810028.46159.131510059.42162.9441
10076.08168.767910085.17171.088610098.05 171.92710110.93174.646210123.69173.1814
10136.68179.278210149.56181.030310171.31180.247310201.61181.120510237.22180.7845
#Mann= 3 , 0 , 0
9449.122    0.04       09449.122    0.04       010237.22    0.04       0
#XS Ineff= 2 , 0
       09630.029                       0
Bank Sta=9449.122,10237.22
Exp/Cntr=0.3,0.1

Type RM Length L Ch R = 1 ,5738.794,291.471300,291.471300,291.471300
XS GIS Cut Line= 6
844802.480167061839151.373414829845322.531517735839407.098375224
 845366.50944127839460.212248741845406.727254465839519.560244067
845446.147131647839563.052101207845740.437301159839714.884310812
#Sta/Elev= 30
9317.616173.80869443.003157.47899476.434157.55339487.578159.73459521.008155.8402
9576.726 146.2559621.301145.75689632.444145.98479665.875152.68949688.163151.1519
 9710.45153.24279732.737152.61619777.311156.5157 9866.46152.99699920.382157.4386
9981.227 155.6629983.964155.52929996.046147.7531    9999147.663410045.15153.4494
10079.91152.219910151.48156.607810252.75157.974710275.23160.753210309.01161.2947
10342.77166.416210365.27171.190310376.52175.706710387.78177.493810427.65179.7332
#Mann= 3 , 0 , 0
9317.616    0.04       09317.616    0.04       010427.65    0.04       0
#XS Ineff= 2 , 0
       09894.469                       0
Bank Sta=9317.616,10427.65
Exp/Cntr=0.3,0.1

Type RM Length L Ch R = 1 ,5447.323,145.735600,145.735600,145.735600
XS GIS Cut Line= 6
844872.615741039839327.288345438845106.647434754839500.754371082
845221.590183243 839599.63765882845260.359965432839653.499621599
845286.900025455839733.984207164845706.061908811839754.170473501
#Sta/Elev= 30
9444.836157.34039497.288157.57639534.415153.78589596.292154.28279646.328152.7933
9658.866151.32019671.403146.43369683.941144.78359721.553143.78069759.802140.7616
 9785.57 143.0689811.338 151.6229824.221153.54299837.874151.6947 9893.12151.0599
  9944.5152.12549966.811153.90959977.566 151.9649998.559145.384910008.99 146.753
10019.43152.667110029.88154.114110067.39152.680310137.47 154.773 10247.6153.8241
10397.77164.606310407.79167.358710427.81182.350210447.83184.001810458.91182.7762
#Mann= 3 , 0 , 0
9444.836   0.044       09444.836   0.044       010458.91   0.044       0
#XS Ineff= 2 , 0
       09850.805        10030.85       0
Bank Sta=9444.836,10458.91
Exp/Cntr=0.3,0.1

Type RM Length L Ch R = 1 ,5301.587,102.704600,102.704600,102.704600
XS GIS Cut Line= 6
843885.792608238839281.440249616  844029.1743747839348.449885219
844259.265121758839451.967920363844826.016682953839728.054394394
845476.269208252 839769.08974795846121.786885023839825.907929748
#Sta/Elev= 30
8636.805 248.1568713.198232.84928739.688234.55398757.351229.70618779.427229.2185
8811.038235.32958867.254228.47419042.701193.73559087.127171.5148 9099.97172.4258
9142.744157.74729187.238150.67579365.213148.55879576.557150.69419654.421147.1855
9927.278 153.3839957.337148.40149987.397138.331110007.44137.9232 10037.5148.4559
10057.54 151.69110257.93155.738510338.11153.823510408.38 161.23810488.69164.0868
10538.88177.793210619.19181.247710840.04176.925810940.43166.183510977.36165.2333
#Mann= 3 , 0 , 0
8636.805  0.0552       08636.805  0.0552       010977.36  0.0552       0
#XS Ineff= 2 , 0
       09913.256                       0
Bank Sta=8636.805,10977.36
Exp/Cntr=0.3,0.1