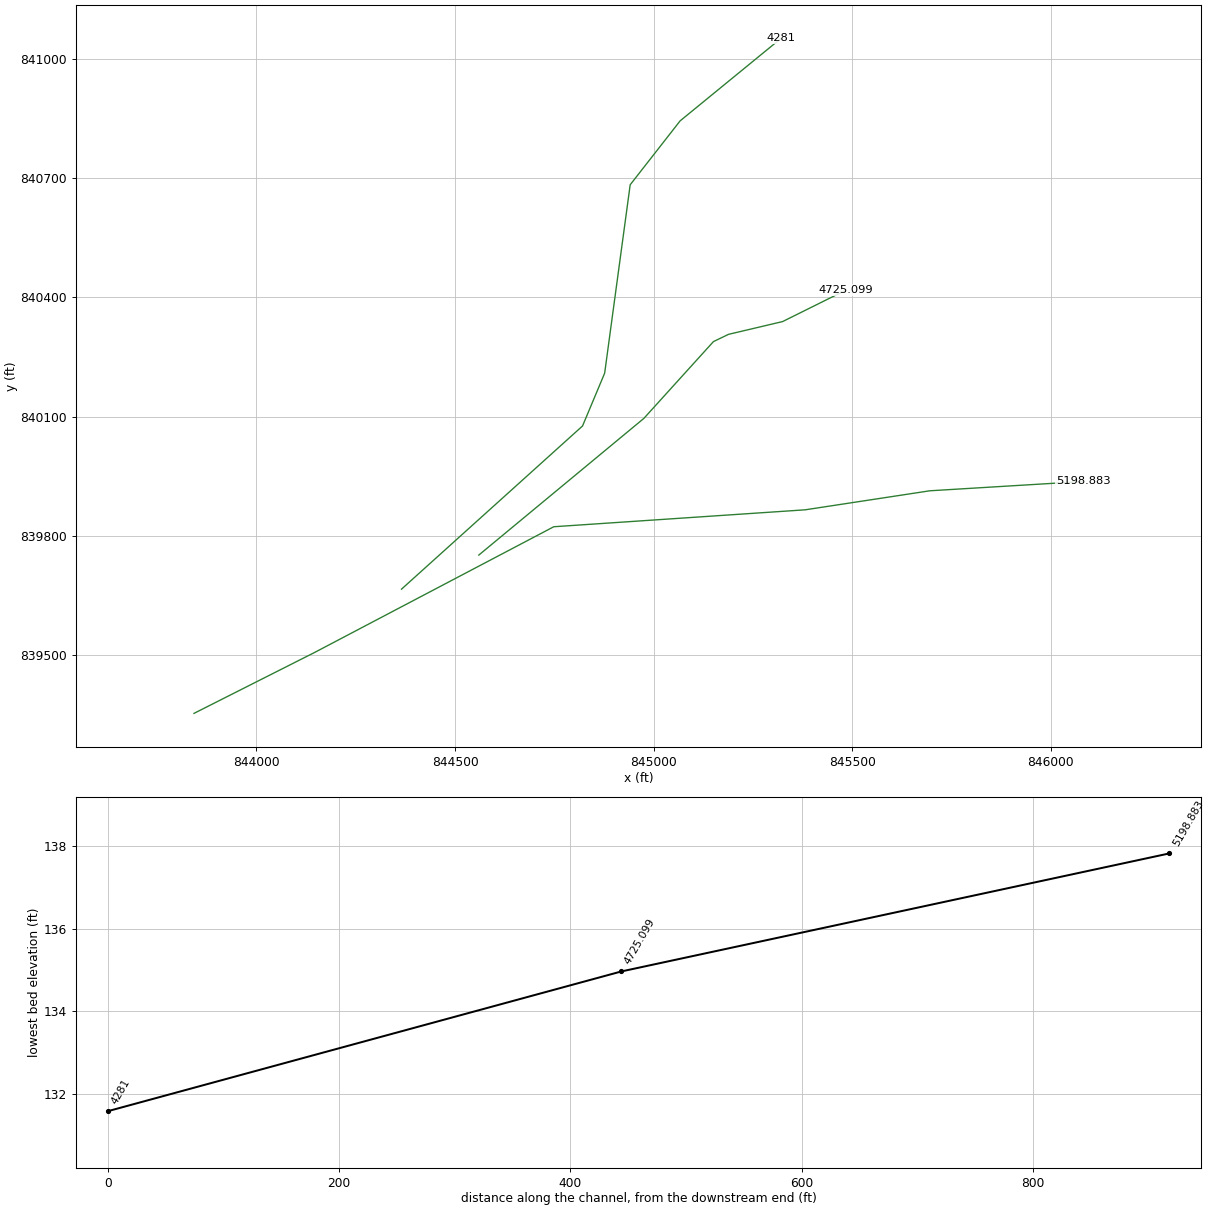
HEC-RAS study 18597_ras.prj: 18597

--- 18597_ras.g01 (geometry) --- (continued)

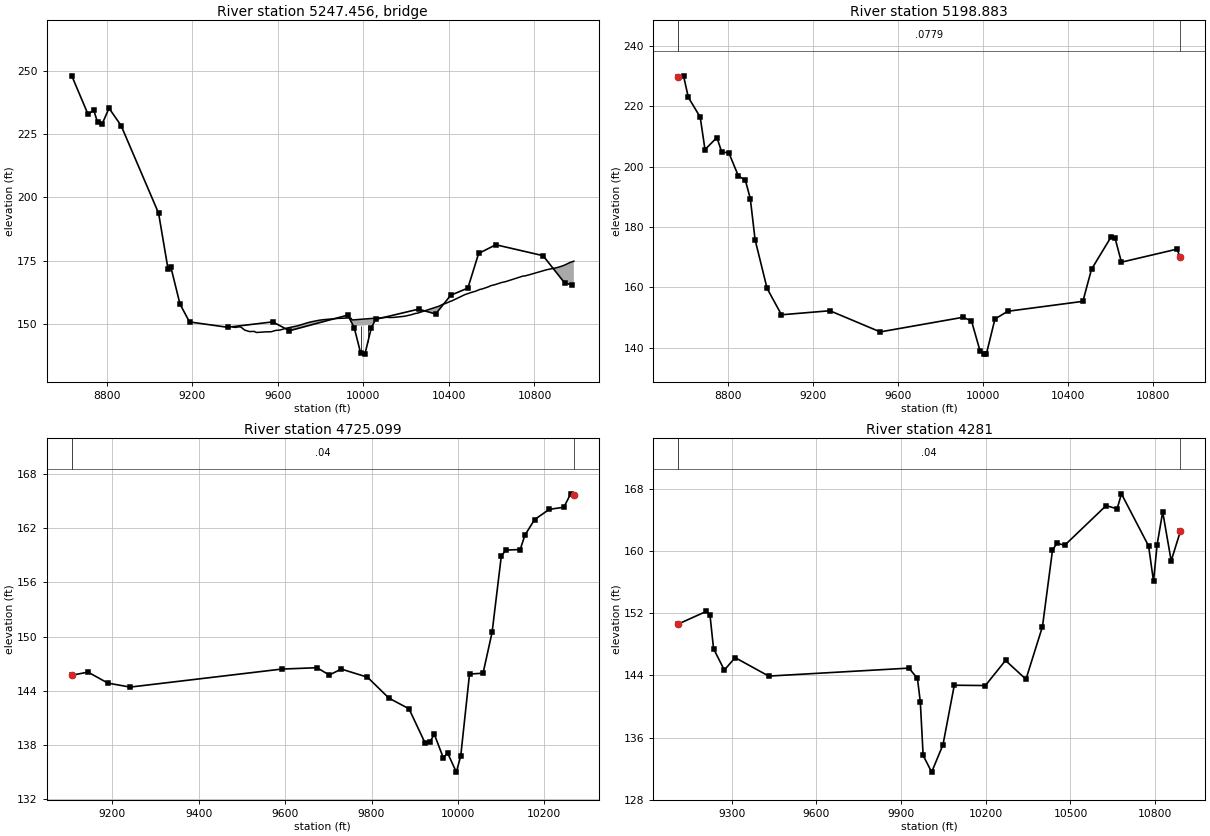
Type RM Length L Ch R = 3 ,5247.456,,,
BEGIN DESCRIPTION:
END DESCRIPTION:
Bridge Culvert--1,0,-1,-1, 0
Deck Dist Width WeirC Skew NumUp NumDn MinLoCord MaxHiCord MaxSubmerge Is_Ogee
40.352300,22.000000,2.6,0, 60, 60, , , 0.95, 0, 0,0,,
 9390.44 9403.50 9414.25 9425.01 9433.85 9435.77 9446.53 9468.04 9489.56 9500.32
 9542.36 9569.49 9589.90 9609.28 9641.58 9691.68 9741.78 9761.82 9791.88 9811.92
 9882.06 9932.19 9942.22 9947.85 9957.12 9957.1210052.1210052.1210112.7110122.74
10142.8010192.9410223.0310243.0910253.1110353.4010373.4810383.5710403.7510413.83
10474.3710504.6410524.8110544.9910555.0810575.2610585.3510595.4410615.6110645.88
10665.9910746.2610756.3010776.3610856.6310896.7710916.8410936.9010967.0010984.12
  148.63  148.50  148.71  148.71  148.24  148.04  147.40  146.86  146.93  146.49
  146.74  146.79  147.31  147.45  148.22  149.12  150.42  150.82  151.32  151.56
  152.08  152.26  152.14  151.46  151.52  151.52  152.14  152.14  152.51  152.42
  152.48  152.93  153.51  154.02  154.14  156.91  157.73  157.96  158.73  159.02
  161.48  162.36  162.84  163.55  163.72  164.30  164.60  165.02  165.44  166.28
  166.66  168.84  168.92  169.37  171.34  172.03  172.46  173.05  174.24  174.75
 -851.37 -851.50 -851.29 -851.29 -851.76 -851.96 -852.60 -853.14 -853.07 -853.51
 -853.26 -853.21 -852.69 -852.55 -851.78 -850.88 -849.58 -849.18 -848.68 -848.44
 -847.92 -847.74 -847.86 -848.54 -848.48  149.02  149.64 -847.86 -847.49 -847.58
 -847.52 -847.07 -846.49 -845.98 -845.86 -843.09 -842.27 -842.04 -841.27 -840.98
 -838.52 -837.64 -837.16 -836.45 -836.28 -835.70 -835.40 -834.98 -834.56 -833.72
 -833.34 -831.16 -831.08 -830.63 -828.66 -827.97 -827.54 -826.95 -825.76 -825.25
 9390.44 9403.50 9414.25 9425.01 9433.85 9435.77 9446.53 9468.04 9489.56 9500.32
 9542.36 9569.49 9589.90 9609.28 9641.58 9691.68 9741.78 9761.82 9791.88 9811.92
 9882.06 9932.19 9942.22 9947.85 9951.92 9951.9210046.9210046.9210112.7110122.74
10142.8010192.9410223.0310243.0910253.1110353.4010373.4810383.5710403.7510413.83
10474.3710504.6410524.8110544.9910555.0810575.2610585.3510595.4410615.6110645.88
10665.9910746.2610756.3010776.3610856.6310896.7710916.8410936.9010967.0010984.12
  148.63  148.50  148.71  148.71  148.24  148.04  147.40  146.86  146.93  146.49
  146.74  146.79  147.31  147.45  148.22  149.12  150.42  150.82  151.32  151.56
  152.08  152.26  152.14  151.46  151.49  151.49  152.11  152.11  152.51  152.42
  152.48  152.93  153.51  154.02  154.14  156.91  157.73  157.96  158.73  159.02
  161.48  162.36  162.84  163.55  163.72  164.30  164.60  165.02  165.44  166.28
  166.66  168.84  168.92  169.37  171.34  172.03  172.46  173.05  174.24  174.75
 -851.37 -851.50 -851.29 -851.29 -851.76 -851.96 -852.60 -853.14 -853.07 -853.51
 -853.26 -853.21 -852.69 -852.55 -851.78 -850.88 -849.58 -849.18 -848.68 -848.44
 -847.92 -847.74 -847.86 -848.54 -848.51  148.99  149.61 -847.89 -847.49 -847.58
 -847.52 -847.07 -846.49 -845.98 -845.86 -843.09 -842.27 -842.04 -841.27 -840.98
 -838.52 -837.64 -837.16 -836.45 -836.28 -835.70 -835.40 -834.98 -834.56 -833.72
 -833.34 -831.16 -831.08 -830.63 -828.66 -827.97 -827.54 -826.95 -825.76 -825.25
Pier Skew, UpSta & Num, DnSta & Num=  ,9988.28, 2 ,9983.09, 2 , 0 , 0 , 0 ,,
    3.00    3.00
 -848.28  151.72
    3.00    3.00
 -848.31  151.69
Pier Skew, UpSta & Num, DnSta & Num=  ,10020.95, 2 ,10015.75, 2 , 0 , 0 , 0 ,,
    3.00    3.00
 -848.06  151.94
    3.00    3.00
 -848.10  151.90
BR Coef=-1 , 0 , 0 ,, 0 ,,,0.8,0,1,0,
WSPro=,,,, 1 ,,,, 0 ,,,, 0 ,,,,-1 ,-1 ,-1 , 0 , 0 , 0 , 0 , 0
BC Design=,, 0 ,, 0 ,,,,,,

Type RM Length L Ch R = 1 ,5198.883,473.783400,473.783400,473.783400
XS GIS Cut Line= 6
843842.794383615839352.848015577844147.771027714839506.875641555
844748.680824399839822.751364082845381.572238535839865.365000457
845695.666111827839913.277625173 846081.17945832839936.653421283
#Sta/Elev= 30
8568.111229.62538592.988 230.0978615.394222.98638671.409216.37758693.815205.6431
 8749.83209.64278772.236204.83538805.845204.58048850.657 196.8998883.434195.4731
8906.672189.39598929.197175.74658985.558 159.6139053.192150.87279280.488152.2117
9517.097 145.1989905.732150.03719945.823148.86419985.914138.926910005.96137.8291
10015.98137.922510056.07149.473410116.21 152.03710469.27155.329310509.73 165.957
10600.19176.513610620.23176.345210650.28168.312110910.76172.627510926.97169.8925
#Mann= 3 , 0 , 0
8568.111  0.0779       08568.111  0.0779       010926.97  0.0779       0
#XS Ineff= 2 , 0
       09916.316                       0
Bank Sta=8568.111,10926.97
Exp/Cntr=0.3,0.1

Type RM Length L Ch R = 1 ,4725.099,444.099200,444.099200,444.099200
XS GIS Cut Line= 6
844559.880597871839751.415084205844975.461067471840095.537285533
845150.632127684840288.895154839 845188.59230233840307.159471179
845324.693647519840339.281102475845484.983973784 840418.85904773
#Sta/Elev= 30
 9105.68145.70679143.221146.0562 9189.38144.83649240.793144.39499591.647146.3918
9673.562146.54429702.264145.73289729.797146.3958 9790.52 145.4929840.133143.1759
9886.748141.98619923.543138.23559934.623138.27539945.344139.16019966.063136.5614
9976.205137.07169996.398134.963810006.56136.768810026.88145.841610058.23145.9336
 10079.2150.482410100.61158.966810111.52159.591810144.25159.649210155.16161.2416
10177.46162.965510211.45164.105810245.44164.342210261.08165.8289 10268.5165.6568
#Mann= 3 , 0 , 0
 9105.68    0.04       0 9105.68    0.04       0 10268.5    0.04       0
#XS Ineff= 2 , 0
       0                               0
Bank Sta=9105.68,10268.5
Exp/Cntr=0.3,0.1

Type RM Length L Ch R = 1 ,    4281,0.000000,0.000000,0.000000
XS GIS Cut Line= 6
 844365.28840461839665.634526884844821.046756138840076.462658005
844876.746858528840209.430027754844941.006335819840683.723324221
845066.802653218840844.702149809845320.879791037 841052.42156454
#Sta/Elev= 30
 9110.92150.60339210.922152.23349223.468151.72539236.013147.42959274.143144.6832
9312.446146.28299431.358143.91229927.988 144.936 9958.16143.60949968.218140.5975
9978.275133.720610008.43131.570610048.52135.091210088.54142.737610198.64142.6961
10270.03145.922410342.36143.505310400.86150.274310436.31160.059810451.81161.0022
10479.32160.713110626.23165.815710665.32165.4055 10680.5167.332810776.67160.6357
 10794.2156.0832 10806.7160.751710826.67165.0209 10856.7158.716210889.05162.4924
#Mann= 3 , 0 , 0
 9110.92    0.04       0 9110.92    0.04       010889.05    0.04       0
#XS Ineff= 2 , 0
       0                               0
Bank Sta=9110.92,10889.05
Exp/Cntr=0.3,0.1